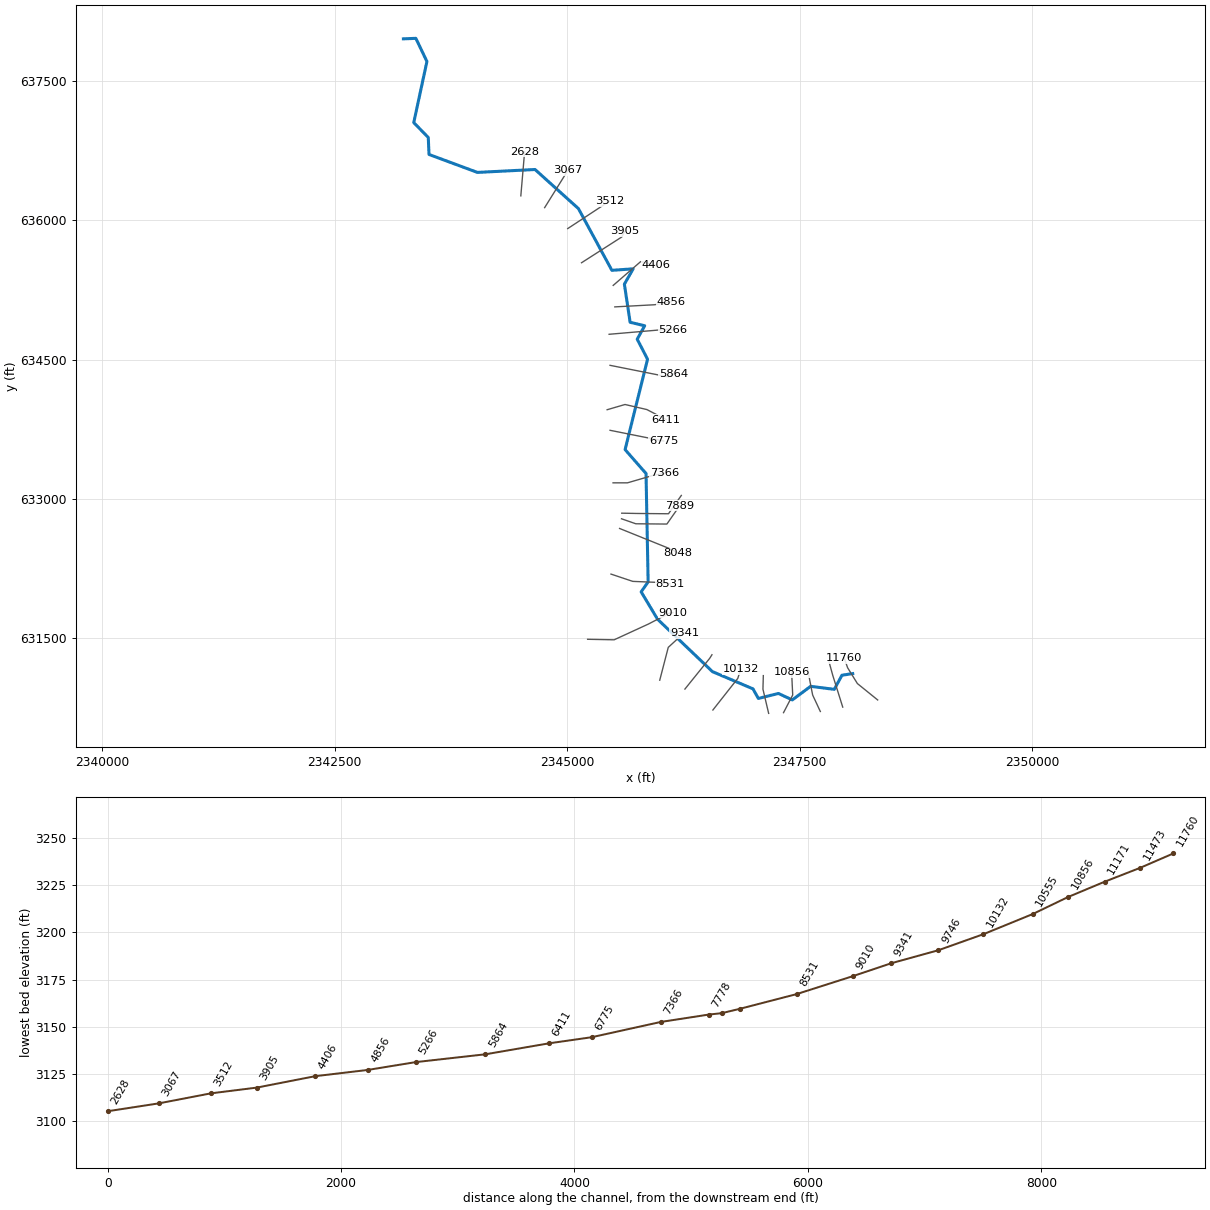
--- FIVELCKRN.prj (project) ---

Proj Title=FIVELCKRN
Current Plan=p01
Default Exp/Contr=0,0
English Units
Geom File=g01
Flow File=f01
Plan File=p01
Background Map Layer=Inundation Boundary (P100yr Value_0)
Background Map Layer=Inundation Boundary (P100yr Value_0)
BEGIN DESCRIPTION:
----------MODEL BY WOOD PLC 2022----------
AFH study
Randolph County, WV
HEC-RAS Version: RAS 6.2
Vertical Datum: NAVD88
Projection: NAD 1983 StatePlane West Virginia S FIPS 4702 (US Feet)
Terrain: 1-meter LIDAR (FEMA Region III 3DEP collected 2016-2018)
Land Use: 2019 NLCD
Hydrologic Method:
WV SIR2010-5033 regression equations
Additional Model Notes:
None
END DESCRIPTION:
DSS Export Rating Curves= 0
DSS Export Rating Curve Sorted= 0
DSS Export Volume Flow Curves= 0
DXF OffsetX= 0
DXF OffsetY= 0
DXF ScaleX= 0
DXF ScaleY= 0

--- FIVELCKRN.p01 (plan) ---

Plan Title=Floodplain
Program Version=6.20
Short Identifier=Floodplain
Geom File=g01
Flow File=f01
Subcritical Flow
K Sum by GR= 0
Std Step Tol= 0.01
Critical Tol= 0.01
Num of Std Step Trials= 20
Max Error Tol= 0.3
Flow Tol Ratio= 0.001
Split Flow NTrial= 30
Split Flow Tol= 0.02
Split Flow Ratio= 0.02
Log Output Level= 0
Friction Slope Method= 1
Unsteady Friction Slope Method= 2
Unsteady Bridges Friction Slope Method= 1
Parabolic Critical Depth
Global Vel Dist= 0 , 0 , 0
Global Log Level= 0
CheckData=True
Encroach Param=-1 ,0,0, 0
Mapping Interval=1HOUR
Computation Time Step Use Courant=        0
Computation Time Step Use Time Series=    0
Computation Time Step Count To Double=0
Computation Time Step Max Doubling=0
Computation Time Step Max Halving=0
Computation Time Step Residence Courant=0
Run HTab= 0
Run UNet= 0
Run Sediment= 0
Run PostProcess= 0
Run WQNet= 0
Run RASMapper=-1
UNET Theta= 0
UNET Theta Warmup= 0
UNET ZTol= 0
UNET ZSATol= 0
UNET MxIter= 0
UNET Max Iter WO Improvement= 0
UNET MaxInSteps= 0
UNET DtIC= 0
UNET DtMin= 0
UNET MaxCRTS= 0
UNET WFStab= 0
UNET SFStab= 0
UNET WFX= 1
UNET SFX= 1
UNET Gravity=32.174
UNET 1D Methodology=Finite Difference
UNET DSS MLevel= 1
UNET Pardiso=0
UNET DZMax Abort= 0
UNET Use Existing IB Tables= 0
UNET Froude Reduction=False
UNET Froude Limit= 0
UNET Froude Power= 0
UNET D1 Cores= 0
UNET WindReference=Eulerian
UNET WindDragFormulation=Hsu (1988)
UNET D2 Coriolis=0
UNET D2 Cores= 0
UNET D2 Theta= 1
UNET D2 Theta Warmup= 1
UNET D2 Z Tol= 0.01
UNET D2 Volume Tol= 0.01
UNET D2 Max Iterations= 20
UNET D2 Equation= 0
UNET D2 RampUpFraction=0.1
UNET D2 TimeSlices= 1
UNET D2 Turbulence Formulation=Non-Conservative (original)
UNET D2 Eddy Viscosity=0.3
UNET D2 Transverse Eddy Viscosity=0.1
UNET D2 Smagorinsky Mixing=0
UNET D2 BCVolumeCheck=0
UNET D2 Cores=0
UNET D2 SolverType=PARDISO (Direct)
UNET D2 Minimum Iterations= 2147483647
UNET D2 Maximum Iterations= 2147483647
UNET D2 Restart Number= 10
UNET D2 Relaxation Coeff=1.3
UNET D2 SOR Precondition Iterations= 10
UNET D2 ILUT Maximum Fill= 8
UNET D2 ILUT Tolerance=1E-08
UNET D1D2 MaxIter= 0
UNET D1D2 ZTol=0.01
UNET D1D2 QTol=0.1
UNET D1D2 MinQTol=1
Write IC File= 0
Write IC File at Fixed DateTime=0
Write IC File at Sim End=0
Echo Input=False
Echo Parameters=False
Echo Output=False
Write Detailed= 0
HDF Write Warmup=0
HDF Write Time Slices=0
HDF Flush=0
HDF Compression= 1
HDF Chunk Size= 1
HDF Spatial Parts= 1
HDF Use Max Rows=0
HDF Fixed Rows= 1
Calibration Method= 0
Calibration Iterations= 20
Calibration Max Change=0.05
Calibration Tolerance=0.2
Calibration Maximum=1.5
Calibration Minimum=0.5
Calibration Optimization Method= 1
WQ AD Non Conservative
WQ ULTIMATE=-1
WQ Max Comp Step=1HOUR
WQ Output Interval=15MIN
WQ Output Selected Increments= 0
WQ Output face flow=0
WQ Output face velocity=0
WQ Output face area=0
WQ Output face dispersion=0
WQ Output cell volume=0
WQ Output cell surface area=0
WQ Output cell continuity=0
WQ Output cumulative cell continuity=0
WQ Output face conc=0
WQ Output face dconc_dx=0
WQ Output face courant=0
WQ Output face peclet=0
WQ Output face adv mass=0
WQ Output face disp mass=0
WQ Output cell mass=0
WQ Output cell source sink temp=0
WQ Output nsm pathways=0
WQ Output nsm derived pathways=0
WQ Create Restart=0
WQ Fixed Restart=0
WQ System Summary=0
WQ Write To DSS=0
Sorting and Armoring Iterations= 10
XS Update Threshold= 0.02
Bed Roughness Predictor= 0
Hydraulics Update Threshold= 0.02
Energy Slope Method= 1
Volume Change Method= 1
Sediment Retention Method= 0
Sediment TS Multiplier= 1
Warm Up Method= 0
XS Weighting Method= 0
Number of US Weighted Cross Sections= 1
Number of DS Weighted Cross Sections= 1
Upstream XS Weight=0
Main XS Weight=1
Downstream XS Weight=0
Number of DS XS's Weighted with US Boundary= 1
Upstream Boundary Weight= 1
Weight of XSs Associated with US Boundary= 0
Number of US XS's Weighted with DS Boundary= 1
Downstream Boundary Weight= 0.5
Weight of XSs Associated with DS Boundary= 0.5
Percentile Method= 0
Sediment Output Level= 3
Mass or Volume Output= 0
Output Increment Type= 1
Profile and TS Output Increment= 1
Transport Output Increment 1
XS Output Flag= 0
XS Output Increment= 10
Read HDF5 Sediment Hotstart= 0
Sediment Hotstart Type= 0
Write Gradation File= 0
Read Gradation Hotstart= 0
Write HDF5 File= 1
Write Binary Output= 1
Write DSS Sediment File= 0
DSS Sediment Output Type= 1
SV Curve= 0
Specific Gage Flag= 0
Subcell Erosion Methods= 0
Subcell Deposition Methods= 0
Advection Scheme= 1
Matrix Solver= 0
Implicit Weighting Factor= 1
Maximum Outer Loop Convergence Iterations= 5
Convergence Maximum Absolute= 0.001
Convergence RMSE= 0.0001
Grain Fractions Max Abs Error= 0.001
Max Subgrid Regions= 1
Max Subgrid Length Scale= 3.402823E+38
Initial Layer Thickness= 3.402823E+38
Min Layer Thickness= 3.402823E+38
Max Layer Thickness= 3.402823E+38
Number of Layers= 5

--- FIVELCKRN.f01 (steady flow) ---

Flow Title=Flow
Program Version=4.00
Number of Profiles=1
Profile Names=P100yr
River Rch & RM=FIVELCKRN,Main,11760
     523
River Rch & RM=FIVELCKRN,Main,9341
     617
River Rch & RM=FIVELCKRN,Main,8048
     722
River Rch & RM=FIVELCKRN,Main,3905
     897
Boundary for River Rch & Prof#=FIVELCKRN,Main      ,1
Up Type=0
Dn Type=3
Dn Slope=0.013717

--- FIVELCKRN.g01 (geometry) ---

Geom Title=Geometry
Program Version=6.20

River Reach=FIVELCKRN       ,Main
Reach XY= 30
2348070.59800003631121.4400000132347954.74200004      631103.912
 2347872.8219374630951.973426854     2347618.358630984.555000022
2347421.16000003630838.4179999982347271.84200001630907.905000001
2347056.21700005 630854.086000012346998.57800001630957.210999995
2346562.58800001631142.7290000022345972.49600004631706.704999998
2345796.35100003632000.8770000042345871.41499999632108.069000006
2345848.79000002633274.2140000022345623.66800001633531.217000008
     2345865.096634503.4050000012345753.98400001634719.377000019
2345834.33000001634863.6870000062345677.86800003634900.898000002
2345616.04300004635311.3129999942345710.64732049635476.040583082
     2345481.417635459.9979999962345122.27400002636123.837000012
2344655.59499998636544.7070000172344036.38200004      636513.419
2343515.56400004636706.5039999932343507.98300003636888.884000003
2343351.74600002637049.3570000082343493.36900002637706.694999993
     2343374.338637955.8150000132343240.51404364637950.184341806

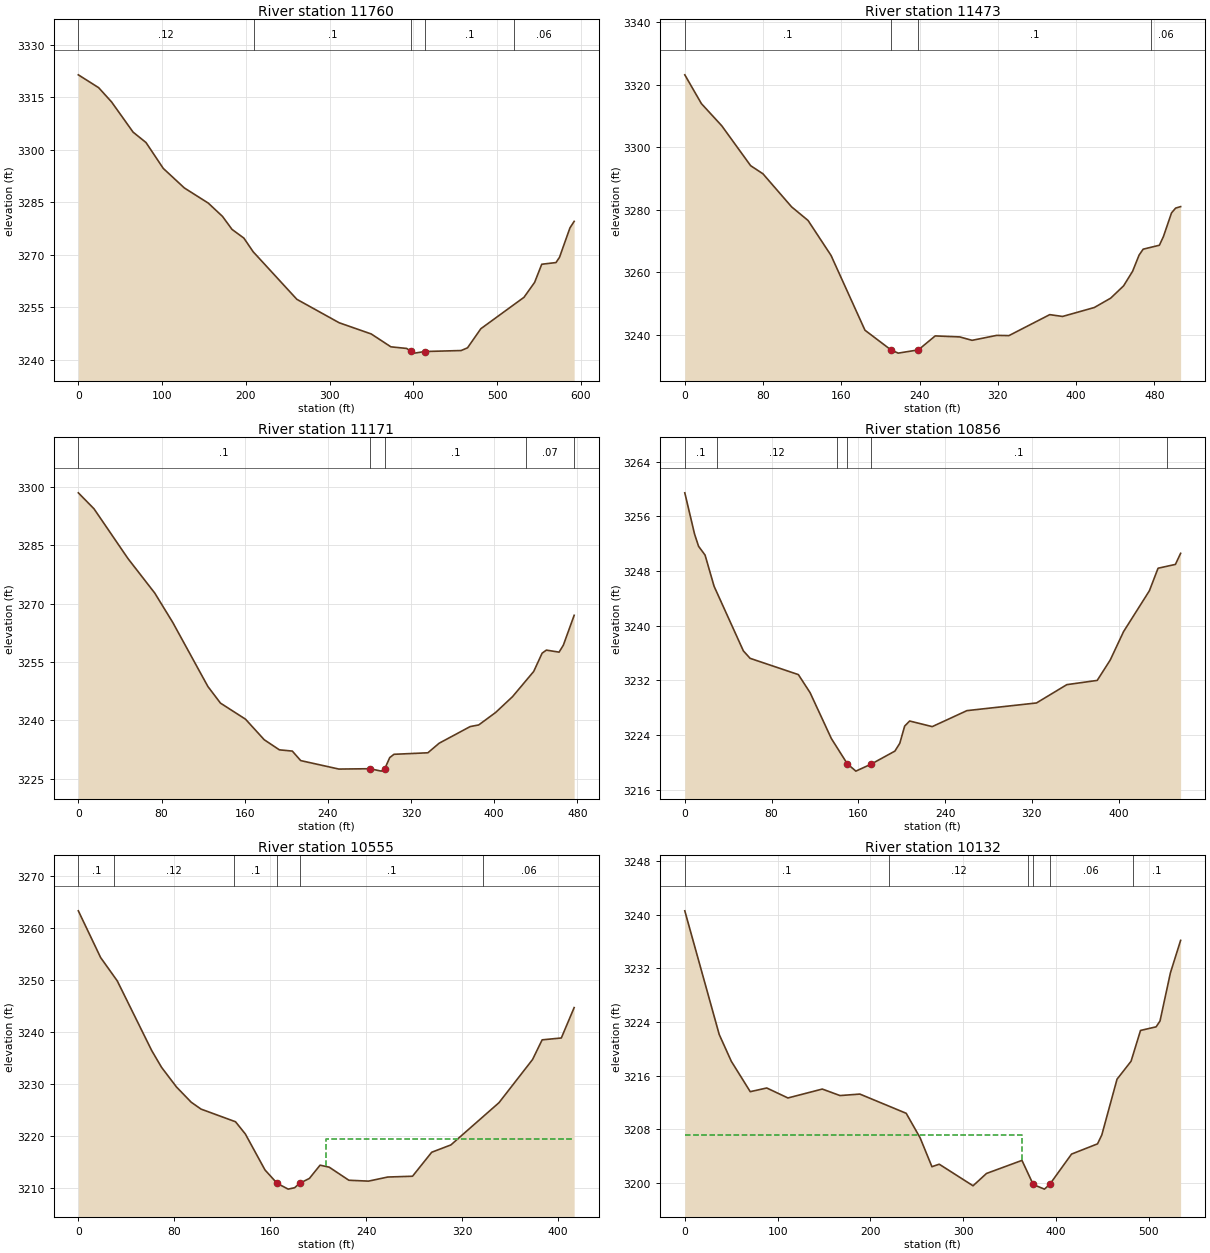
Type RM Length L Ch R = 1 ,11760   ,285.8,286.7,263.9
XS GIS Cut Line= 4
2348339.01305418630837.9150177022348120.85371604631014.433984247
2348015.84756158631184.6163725062347978.73331733631289.622526963
#Sta/Elev= 30
       0 3321.42    24.3 3317.74    39.7 3313.67    65.4 3305.04    80.8 3302.07
   101.4 3294.68   126.6 3289.09   155.1 3284.77   172.1 3280.97   183.5 3277.25
   197.7 3274.75   208.7 3270.87   260.9 3257.27   311.5 3250.56   349.7 3247.37
   373.2 3243.69     392 3243.23   397.4 3242.37   401.4 3241.89   413.9 3242.35
   457.1 3242.63   464.7 3243.41   480.6 3248.87   532.1 3257.84   544.8 3262.11
   553.3 3267.29   570.3 3267.77   574.5 3269.27     587 3277.69     592 3279.54
#Mann= 5 ,-1,0
       0     .12       0     210      .1       0   397.4    .045       0
   413.9      .1       0   520.6     .06       0
Bank Sta=397.4,413.9
XS Rating Curve= 0 ,0
Exp/Cntr(USF)=0,0
Exp/Cntr=0.3,0.1

Type RM Length L Ch R = 1 ,11473   ,299.7,301.8,292.6
XS GIS Cut Line= 3
2347963.34448435630760.9708527982347856.52787895631101.335629315
 2347816.6979583631246.171704429
#Sta/Elev= 30
       0 3323.14      17 3313.93    37.8 3306.85    67.3 3294.11    79.9 3291.51
   109.2 3280.94     126  3276.6   149.5 3265.43   184.2 3241.52     211 3235.18
   218.2  3234.2   238.8 3235.24     256  3239.7   281.1 3239.38   293.7 3238.29
   318.8 3239.87   331.4  3239.8   373.1  3246.5   386.2 3245.92   418.7 3248.78
   435.4 3251.77   448.6  3255.7   457.8 3260.36   464.4 3265.51   468.6 3267.42
   485.2 3268.68   489.3 3271.44   497.6 3279.02   501.8 3280.55   506.9 3281.02
#Mann= 4 ,-1,0
       0      .1       0     211    .045       0   238.8      .1       0
  476.73     .06       0
Bank Sta=211,238.8
XS Rating Curve= 0 ,0
Exp/Cntr(USF)=0,0
Exp/Cntr=0.3,0.1

Type RM Length L Ch R = 1 ,11171   ,316.6,315.5,299
XS GIS Cut Line= 4
2347722.55450947630713.8991283862347640.17899175630890.418094931
2347613.92745314631023.4862389422347586.77068905631167.417088586
#Sta/Elev= 30
       0 3298.54    15.1 3294.42    47.8  3281.6    73.5 3272.74    90.8 3265.19
   124.6 3248.69   136.7 3244.41   160.8 3240.27   178.8 3234.98   193.4 3232.38
   205.8 3232.06   213.9 3229.61   250.6 3227.43   280.4 3227.52   291.4  3226.9
   294.8 3227.55   299.5 3230.38   303.6 3231.23   336.2 3231.62   347.1 3234.09
   376.9 3238.37   385.1 3238.79   401.3 3241.98   417.6 3246.06     438 3252.56
   446.1 3257.27   450.2 3258.05   462.4 3257.53   466.5 3259.32   476.9 3267.01
#Mann= 5 ,-1,0
       0      .1       0   280.4    .045       0   294.8      .1       0
  430.43     .07       0   476.9     .06       0
Bank Sta=280.4,294.8
XS Rating Curve= 0 ,0
Exp/Cntr(USF)=0,0
Exp/Cntr=0.3,0.1

Type RM Length L Ch R = 1 ,10856   ,296.3,301,310.3
XS GIS Cut Line= 3
2347326.97097932630701.2259718132347425.64055549  630891.3233204
2347413.87262439631133.923746216
#Sta/Elev= 30
       0 3259.44       9 3253.41    12.7 3251.62    18.7 3250.33      27 3245.77
      54 3236.32    60.2 3235.23   104.7 3232.85   115.5 3230.21   135.1  3223.5
  149.79 3219.81   149.83219.807   157.7 3218.73  171.99 3219.77     1723219.771
   193.7 3221.66   198.2  3222.8   202.7 3225.32   207.3 3226.06   228.1 3225.24
   260.1 3227.58   324.2  3228.7   352.2 3231.38   380.2    3232   392.2 3234.98
   404.5 3239.14   428.3 3245.11   436.3 3248.41   452.3 3248.97   457.1 3250.59
#Mann= 6 ,-1,0
       0      .1       0      30     .12       0     140      .1       0
  149.79    .045       0  171.99      .1       0  444.18     .06       0
Bank Sta=149.8,172
XS Rating Curve= 0 ,0
Exp/Cntr(USF)=0,0
Exp/Cntr=0.3,0.1

Type RM Length L Ch R = 1 ,10555   ,426.7,423.3,409.3
XS GIS Cut Line= 3
2347166.99193493630693.5793621552347105.63776422630954.083136144
2347109.66098853631099.925017335
#Sta/Elev= 30
       0 3263.33    18.6 3254.33    32.5 3249.83    61.2 3236.43    69.4  3233.2
    81.8 3229.43    94.1 3226.49   102.3 3225.16   131.1 3222.72   139.3 3220.36
   155.7 3213.43  165.78 3210.87   165.83210.865     175 3209.75   180.4 3210.02
   184.5 3210.86   192.7 3211.81   201.6 3214.36   209.2 3213.98   225.6 3211.46
     242 3211.29   258.1 3212.08   278.7 3212.23   294.7 3216.85   310.7 3218.26
   350.8 3226.39   378.8  3234.7   386.8 3238.49   402.8 3238.85   413.5  3244.7
#Mann= 6 ,-1,0
       0      .1       0      30     .12       0     130      .1       0
  165.78    .045       0   184.5      .1       0  337.63     .06       0
#XS Ineff= 2 , 0
                          206.61         3219.35
Permanent Ineff=
       F       F
Bank Sta=165.8,184.5
XS Rating Curve= 0 ,0
Exp/Cntr(USF)=0,0
Exp/Cntr=0.3,0.1

Type RM Length L Ch R = 1 ,10132   ,384.9,385.3,384.4
XS GIS Cut Line= 3
2346567.53151293630729.7883809332346835.07592946 631069.75083502
2346866.25591785631166.308218429
#Sta/Elev= 30
       0  3240.6    37.1 3222.13    50.1 3218.14    70.5  3213.6    88.3 3214.15
   111.1 3212.66   148.1 3213.99   167.2 3213.02   188.6 3213.24   238.5 3210.37
   253.5 3206.71   266.2  3202.4   274.1 3202.77   310.5 3199.55     325 3201.39
   363.2 3203.34   375.33199.747  375.36 3199.73   387.4 3199.05   393.1 3199.76
   416.6 3204.28   444.6 3205.81   449.2 3207.14   465.6 3215.46   480.7 3218.14
   490.9 3222.74   507.7 3223.28   511.9 3224.15   523.1 3231.34   534.1 3236.19
#Mann= 6 ,-1,0
       0      .1       0     220     .12       0     370     .06       0
  375.36    .045       0   393.1     .06       0  482.61      .1       0
#XS Ineff= 2 , 0
          362.84 3207.12
Permanent Ineff=
       F       F
Bank Sta=375.3,393.1
XS Rating Curve= 0 ,0
Exp/Cntr(USF)=0,0
Exp/Cntr=0.3,0.1

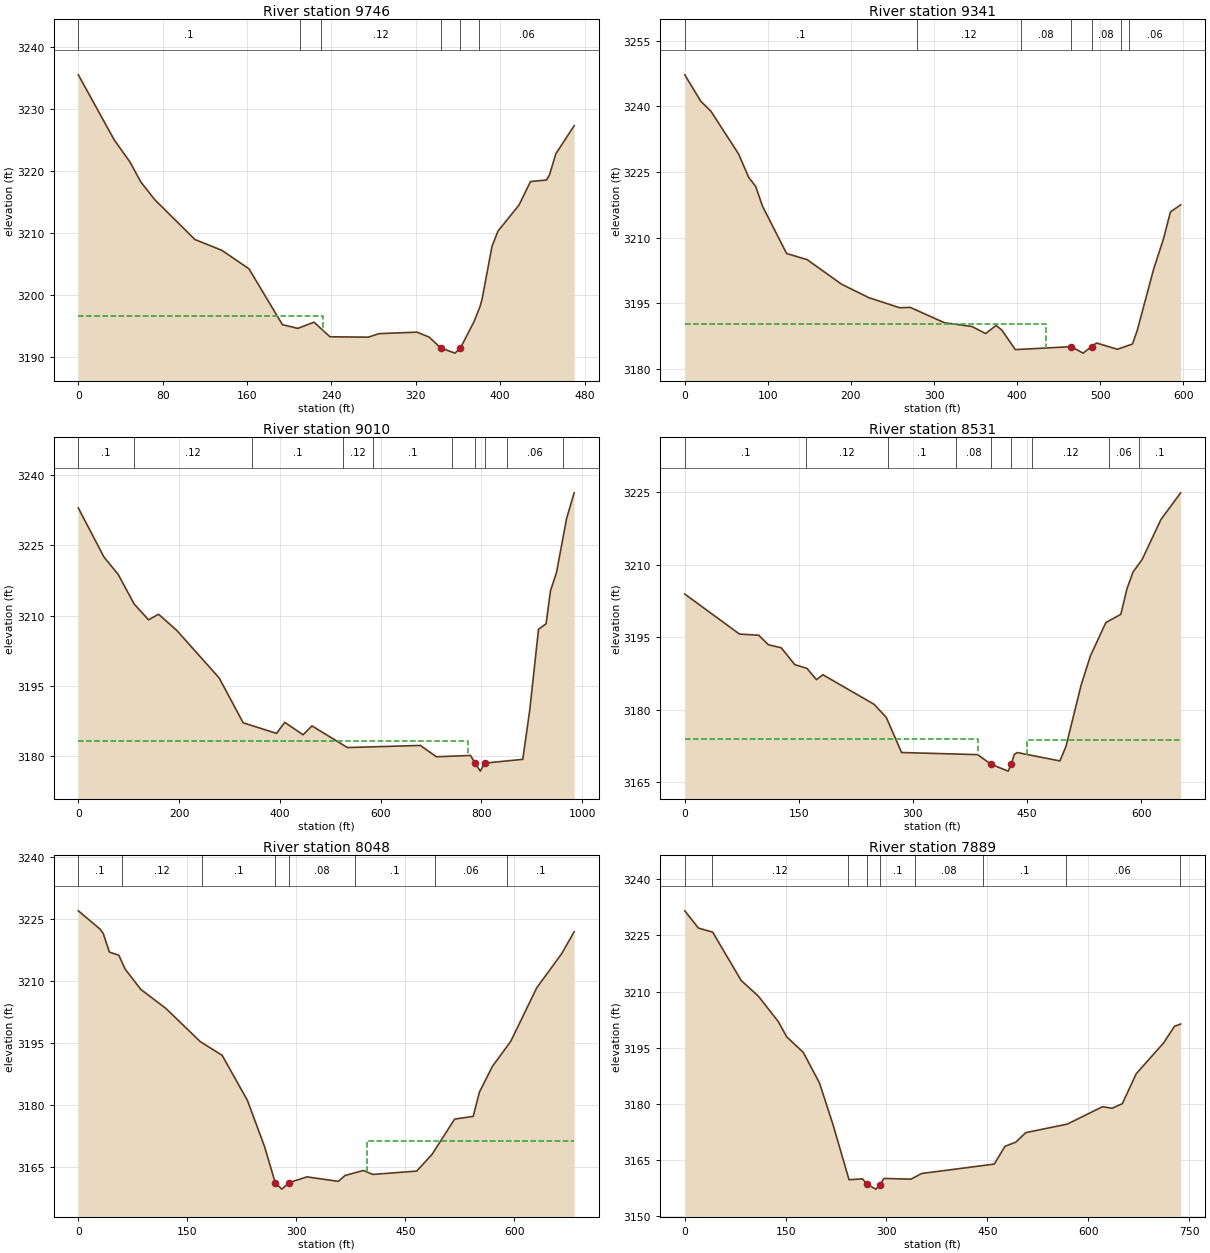
Type RM Length L Ch R = 1 ,9746    ,406.7,404.8,403
XS GIS Cut Line= 3
2346266.79549586630955.0889422212346533.33410631631285.999141614
2346557.47345216631324.219772546
#Sta/Elev= 30
       0 3235.51    34.1 3224.98    48.9 3221.44    59.4 3218.17    72.3 3215.37
   110.5 3208.91   136.1 3207.16   161.8 3204.17   193.5 3195.15   208.1 3194.55
   223.5 3195.55   238.6 3193.19   274.9 3193.13   285.2  3193.7   321.1 3193.94
   332.5 3193.15   343.8 3191.36   357.1 3190.55   362.2 3191.36   375.1 3195.61
   380.8 3198.05   382.8 3199.27   392.2  3207.8   397.9 3210.27   417.8 3214.47
   428.7 3218.27   443.8 3218.52   446.7 3219.33   452.7 3222.75   470.1 3227.29
#Mann= 6 ,-1,0
       0      .1       0     210     .08       0     230     .12       0
   343.8    .045       0   362.2     .12       0     380     .06       0
#XS Ineff= 2 , 0
          232.24 3196.53
Permanent Ineff=
       F       F
Bank Sta=343.8,362.2
XS Rating Curve= 0 ,0
Exp/Cntr(USF)=0,0
Exp/Cntr=0.3,0.1

Type RM Length L Ch R = 1 ,9341    ,331.7,331.3,328.2
XS GIS Cut Line= 4
2345996.23366109631050.6405195542346087.76201412631403.678452644
2346234.60970139631538.4564669862346261.76646547631556.560976375
#Sta/Elev= 30
       0  3247.2    19.2 3241.18    31.5 3238.88    64.6 3229.16      77 3223.75
    85.3 3221.72    93.5 3217.21   122.5 3206.39   147.3 3204.98   188.6 3199.38
   221.6 3196.29   258.8 3193.99   271.2 3194.09   312.5 3190.57   345.6 3189.71
   362.1  3188.1   374.6 3189.96   381.6 3188.88   397.8 3184.43   465.1 3185.11
   479.3 3183.63   489.5 3185.12   495.6 3185.94   520.7 3184.51   538.8 3185.72
   544.4 3188.77   564.2 3202.79   576.2 3209.81   584.4 3215.88   596.7  3217.5
#Mann= 7 ,-1,0
       0      .1       0     280     .12       0  404.71     .08       0
   465.1    .045       0   489.5     .08       0  524.71     .12       0
  534.71     .06       0
#XS Ineff= 2 , 0
          434.14 3190.29
Permanent Ineff=
       F       F
Bank Sta=465.1,489.5
XS Rating Curve= 0 ,0
Exp/Cntr(USF)=0,0
Exp/Cntr=0.3,0.1

Type RM Length L Ch R = 1 ,9010    ,483.7,479.3,471.4
XS GIS Cut Line= 5
2345220.86963019631490.649362386 2345505.8227522631485.054739001
2345875.27824537631654.9655143242346097.56138843  631770.6332132
2346138.79943759 631777.67385574
#Sta/Elev= 30
       0 3232.98    50.8 3222.52    79.3 3218.75   110.6 3212.49   139.3 3209.08
   159.3 3210.27   195.3 3206.83   279.4 3196.68   327.2 3187.07   393.3 3184.81
   409.8 3187.16   446.1 3184.51   463.7 3186.41   534.1 3181.78   678.9 3182.23
   710.7 3179.81   778.3 3180.09   787.33178.483787.31563178.478   797.8 3176.74
   806.7 3178.45806.71563178.454   882.1 3179.26   895.8 3189.66   913.4 3207.07
   928.3 3208.22   937.2 3215.32   948.9 3219.11   969.2 3230.78   984.1 3236.22
#Mann= 10 ,-1,0
       0      .1       0     110     .12       0  345.01      .1       0
  525.01     .12       0  585.01      .1       0  741.66     .08       0
787.3156    .045       0806.7156     .08       0  851.66     .06       0
  962.24     .07       0
#XS Ineff= 2 , 0
          774.13 3183.25
Permanent Ineff=
       F       F
Bank Sta=787.3,806.7
XS Rating Curve= 0 ,0
Exp/Cntr(USF)=0,0
Exp/Cntr=0.3,0.1

Type RM Length L Ch R = 1 ,8531    ,485.5,482.8,479.8
XS GIS Cut Line= 4
2345471.95000842632192.065959538 2345706.3028244632113.613085518
2346069.39881827 632098.525994362346108.62525528632085.450515357
#Sta/Elev= 30
       0 3203.89    71.9 3195.62    97.2 3195.38   109.9 3193.41   126.8 3192.78
   144.7 3189.29   160.5 3188.53   173.1  3186.2   181.6  3187.2     249 3181.08
     265 3178.36     285 3171.12   385.1 3170.68  402.38 3168.72   402.43168.716
   425.2 3167.27   429.2 3168.72   433.2 3170.74   437.2 3171.11   493.2 3169.38
   501.2 3172.41   521.2 3185.13   533.3 3191.11   553.6    3198   573.3  3199.7
   581.3 3204.96   589.3 3208.44   601.3 3211.04   626.1 3219.34   651.9 3224.83
#Mann= 9 ,-1,0
       0      .1       0     160     .12       0  267.14      .1       0
  357.14     .08       0  402.38    .045       0   429.2     .08       0
  457.14     .12       0  557.14     .06       0  597.14      .1       0
#XS Ineff= 2 , 0
          385.42 3173.89  450.31         3173.63
Permanent Ineff=
       F       F
Bank Sta=402.4,429.2
XS Rating Curve= 0 ,0
Exp/Cntr(USF)=0,0
Exp/Cntr=0.3,0.1

Type RM Length L Ch R = 1 ,8048    ,155.2,158.8,162.2
XS GIS Cut Line= 3
2345564.48416752632682.8993252022346137.79363151 632451.56392745
2346191.10135361632416.360714749
#Sta/Elev= 30
       0 3226.97    29.9 3222.54    34.2 3221.52    42.8 3216.97    55.7 3216.22
    64.4 3212.84    85.9 3207.94   120.4 3203.33   167.9 3195.25   197.8 3191.97
   232.6 3181.04   256.2 3169.83   270.9 3161.07     280 3159.53     290 3161.11
   314.5  3162.5   357.7 3161.41   366.8 3162.83   392.2 3164.05   405.1 3163.09
   465.5  3163.9   486.7 3167.98   517.7  3176.5   543.2 3177.16   551.8 3183.05
   569.6 3189.26   594.9 3195.36   630.7 3208.34     665 3216.61   682.1 3221.89
#Mann= 8 ,-1,0
       0      .1       0      60     .12       0     170      .1       0
   270.9    .045       0     290     .08       0     380      .1       0
     490     .06       0     590      .1       0
#XS Ineff= 2 , 0
                          396.54         3171.12
Permanent Ineff=
       F       F
Bank Sta=270.9,290
XS Rating Curve= 0 ,0
Exp/Cntr(USF)=0,0
Exp/Cntr=0.3,0.1

Type RM Length L Ch R = 1 ,7889    ,111.3,111.3,111.3
XS GIS Cut Line= 4
2345585.01704777632787.0975581862345738.98986529 632733.34526981
2346072.91748292632730.3278515792346210.71291549632927.465842706
#Sta/Elev= 30
       0 3231.58    20.3 3226.97    41.5 3225.88    83.8 3212.97   109.3 3208.79
   138.9 3202.01   151.6 3197.88   176.3 3193.72   200.3 3185.58   220.3 3174.51
   244.3 3159.68   264.3 3159.92   271.5 3158.41   284.3 3157.17   290.33158.384
   296.3 3160.03   336.3 3159.83   352.3 3161.35   460.3 3163.87   476.3 3168.63
   492.3 3169.73   507.2 3172.28   568.8 3174.55   621.4 3179.21   635.4 3178.79
   650.8 3180.01   671.3 3187.98   712.2 3196.26   728.3 3200.69   737.5 3201.31
#Mann= 9 ,-1,0
       0      .1       0      40     .12       0  243.09      .1       0
   271.5    .045       0   290.3      .1       0  343.09     .08       0
  443.09      .1       0  567.03     .06       0  737.03      .1       0
Bank Sta=271.5,290.3
XS Rating Curve= 0 ,0
Exp/Cntr(USF)=0,0
Exp/Cntr=0.3,0.1

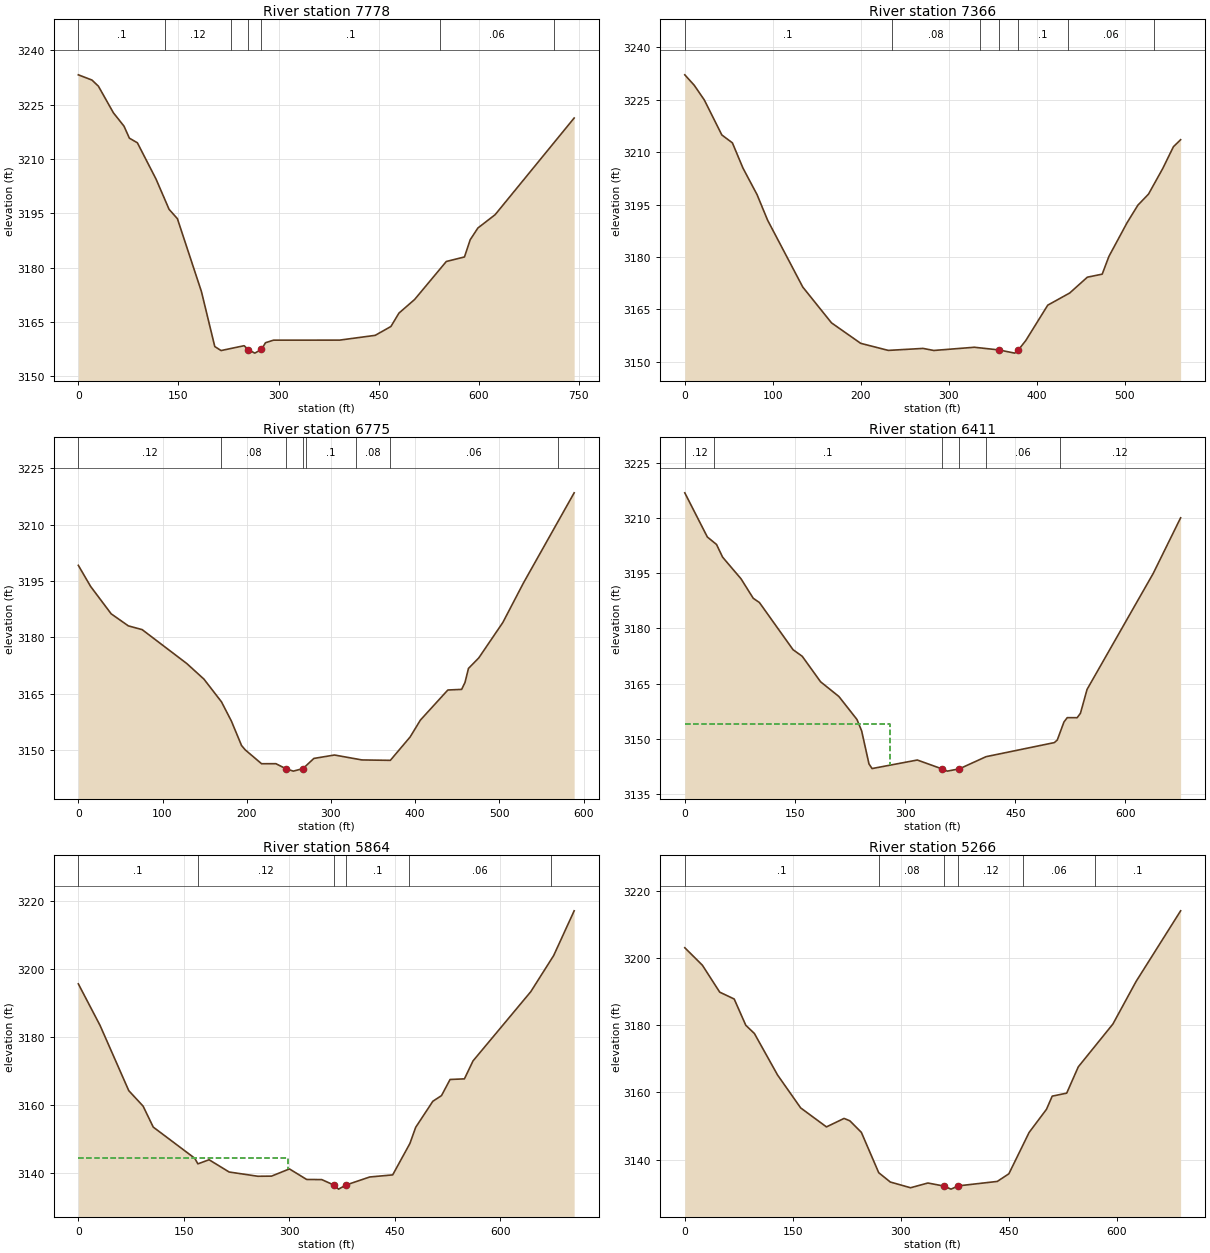
Type RM Length L Ch R = 1 ,7778    ,407.4,411.7,413.5
XS GIS Cut Line= 4
2345587.72935177632847.3637059122345756.36682189632844.122998732
2346090.29443952632841.1055805012346228.08987209633038.243571628
#Sta/Elev= 30
       0 3233.28    20.4 3231.84    30.1 3230.14    52.5 3222.81    68.5 3219.09
    76.5 3215.79    88.5 3214.51   116.5 3204.47     136 3196.14   148.5 3193.54
   184.5 3173.42   204.5 3158.24   213.9 3157.13   248.5 3158.47   254.6 3157.39
   264.5 3156.42   274.5 3157.46   280.5 3159.29   292.5    3160   391.6 3160.01
   444.9 3161.33   468.5 3163.78   480.5 3167.47     504 3171.23   551.5 3181.73
   578.7 3182.98   587.3 3187.73   598.8 3190.97   624.7 3194.66   743.1 3221.35
#Mann= 7 ,-1,0
       0      .1       0     130     .12       0  228.67      .1       0
   254.6    .045       0   274.5      .1       0  542.61     .06       0
  712.61      .1       0
Bank Sta=254.6,274.5
XS Rating Curve= 0 ,0
Exp/Cntr(USF)=0,0
Exp/Cntr=0.3,0.1

Type RM Length L Ch R = 1 ,7366    ,596.7,591.5,588
XS GIS Cut Line= 4
2345494.07774212633173.7326908652345648.97187801633173.732690865
   2345935.62661633257.2145952712346044.25366634633274.313298583
#Sta/Elev= 30
       0 3232.14    10.7 3229.16    22.1 3224.98    42.1 3214.93    54.1 3212.67
    66.1 3205.45    82.1 3197.86    94.1 3190.54   134.1 3171.39   166.7 3161.16
   199.9  3155.3   231.2 3153.28   270.7 3153.85   282.9 3153.26     329 3154.18
   357.1 3153.41   374.9  3152.5     379  3153.4   387.4 3156.08   412.4 3166.22
   437.4 3169.71   457.4 3174.23   474.3  3175.1   481.9 3180.17   502.6 3189.84
   514.8 3194.83   526.9    3198   543.1 3205.34   555.2 3211.56   563.4 3213.57
#Mann= 7 ,-1,0
       0      .1       0  234.89     .08       0  334.89      .1       0
   357.1    .045       0     379      .1       0  434.89     .06       0
  533.46      .1       0
Bank Sta=357.1,379
XS Rating Curve= 0 ,0
Exp/Cntr(USF)=0,0
Exp/Cntr=0.3,0.1

Type RM Length L Ch R = 1 ,6775    ,358.9,363.9,360.4
XS GIS Cut Line= 2
2345461.89194765 633738.995706242346039.22463595633623.328007365
#Sta/Elev= 30
       0 3199.21    14.6 3193.59      39  3186.3    59.4 3183.09    75.8 3182.09
   128.8 3173.06   149.2  3168.9     170 3162.86   181.8 3157.72   193.8 3151.24
   198.1 3150.09   217.6 3146.38   234.6 3146.39   246.63145.046   255.3 3144.41
   266.8 3145.09   279.7 3147.79   304.2  3148.7   336.8 3147.39   370.5 3147.28
     394  3153.5   406.2    3158   438.8 3166.01   455.2 3166.18   459.2 3168.04
   463.3 3171.76   475.5 3174.55   504.1 3183.99   528.6 3194.52   588.8 3218.52
#Mann= 8 ,-1,0
       0     .12       0     170     .08       0   246.6    .045       0
   266.8     .08       0     270      .1       0     330     .08       0
     370     .06       0     570      .1       0
Bank Sta=246.6,266.8
XS Rating Curve= 0 ,0
Exp/Cntr(USF)=0,0
Exp/Cntr=0.3,0.1

Type RM Length L Ch R = 1 ,6411    ,535.1,546.5,537.5
XS GIS Cut Line= 4
2345430.71195926 633960.27304322   2345622.82092634016.598183542
2345857.17373598633962.2846553742346065.37559396633854.663405116
#Sta/Elev= 30
       0 3216.87    30.7 3204.86    43.2 3202.83    51.5 3199.37    76.6 3193.48
    93.2 3188.19   101.6 3187.04   147.4 3174.21   159.9 3172.42   184.9 3165.48
   209.8 3161.49   234.4 3155.24   240.8 3152.13   250.8 3143.14     255 3141.89
   316.6 3144.21   350.43141.784  350.42 3141.78   357.5 3141.19   373.8 3141.81
   410.2 3145.12   503.2 3148.95   507.2 3149.67   516.2 3154.53   520.7 3155.73
   534.2 3155.72   538.7 3156.92   547.7 3163.41   637.8 3194.96   675.1 3210.08
#Mann= 6 ,-1,0
       0     .12       0      40      .1       0  350.42    .045       0
   373.8      .1       0   410.2     .06       0  510.76     .12       0
#XS Ineff= 2 , 0
          279.23 3153.87
Permanent Ineff=
       F       F
Bank Sta=350.4,373.8
XS Rating Curve= 0 ,0
Exp/Cntr(USF)=0,0
Exp/Cntr=0.3,0.1

Type RM Length L Ch R = 1 ,5864    ,585.4,597.8,591.9
XS GIS Cut Line= 3
2345461.89194765 634438.030929882346091.52655196634312.305170233
2346144.83427405634345.496770779
#Sta/Elev= 30
       0 3195.68    30.9 3183.46    71.7  3164.3    92.1 3159.74   106.5 3153.59
   165.5 3144.43     170 3142.79   185.9 3143.99   214.4 3140.39   255.2 3139.14
   274.7 3139.18   300.1  3141.3   324.6  3138.2   346.1 3138.16   363.1 3136.58
   369.9 3135.36     3813136.598  381.02  3136.6   414.3 3138.93   446.9 3139.54
   471.4 3148.78   479.6 3153.52     504 3161.18   516.3 3162.84   528.5 3167.58
   548.9 3167.76   561.1 3173.03   643.2 3193.37   675.8 3204.01   704.9 3217.14
#Mann= 6 ,-1,0
       0      .1       0     170     .12       0   363.1    .045       0
  381.02      .1       0     470     .06       0  672.06     .12       0
#XS Ineff= 2 , 0
          298.47 3144.62
Permanent Ineff=
       F       F
Bank Sta=363.1,381
XS Rating Curve= 0 ,0
Exp/Cntr(USF)=0,0
Exp/Cntr=0.3,0.1

Type RM Length L Ch R = 1 ,5266    ,406.9,410.5,406.4
XS GIS Cut Line= 3
2345451.83388688634771.958547504 2346094.5439702634827.277881749
2346136.78782544634817.219820977
#Sta/Elev= 30
       0 3203.01    24.4 3197.82    48.5  3189.8    68.6 3187.76    84.7 3179.95
    96.7 3177.49   128.8 3165.16   160.9 3155.37   196.7 3149.72   221.2 3152.24
   229.2 3151.53   245.2 3148.09   269.3 3136.09   285.4 3133.32   313.5 3131.62
   337.6 3133.03   359.3 3132.14   369.7 3131.21  379.79 3132.18   379.83132.182
   433.9  3133.5     450 3135.77   478.1 3148.06   502.2 3154.94   510.2 3158.87
   530.3 3159.76   546.4 3167.58   594.5 3180.33   626.6 3192.96   688.5 3213.99
#Mann= 6 ,-1,0
       0      .1       0     270     .08       0   359.3    .045       0
  379.79     .12       0     470     .06       0     570      .1       0
Bank Sta=359.3,379.8
XS Rating Curve= 0 ,0
Exp/Cntr(USF)=0,0
Exp/Cntr=0.3,0.1

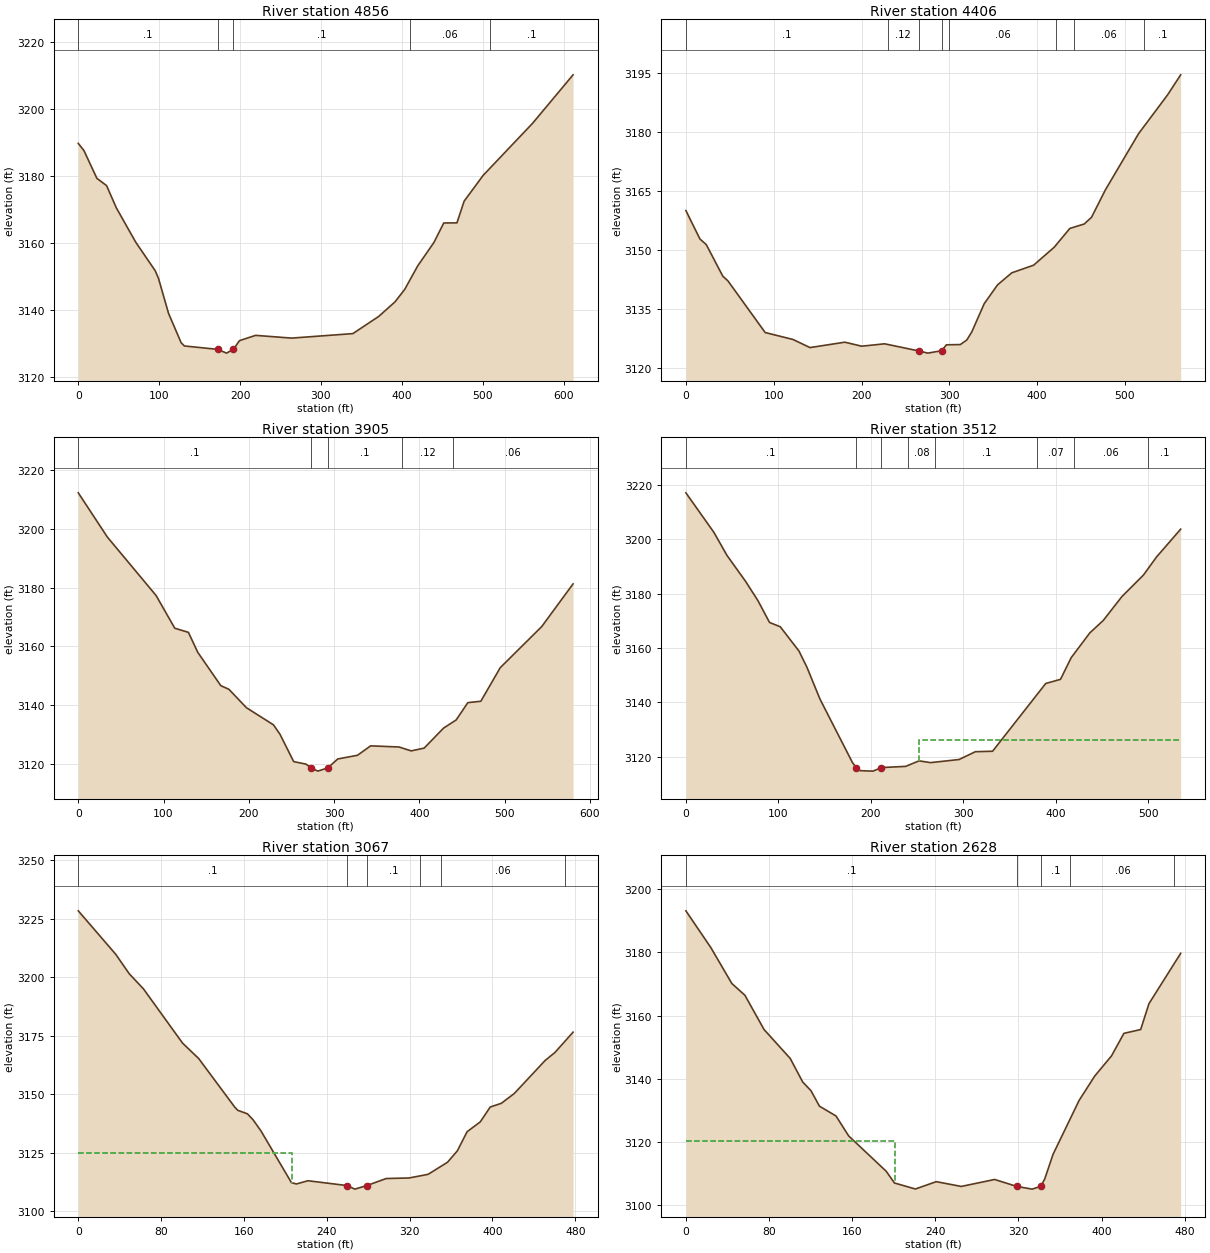
Type RM Length L Ch R = 1 ,4856    ,438.9,450.2,456.1
XS GIS Cut Line= 3
2345513.18805759635066.6597281172345941.66144646635089.793267892
2346121.70073428635120.973256285
#Sta/Elev= 30
       0 3189.62       7 3187.48      23  3179.2      35 3177.03    47.1 3170.37
    71.1 3160.13    95.1 3151.65    99.1 3149.43   111.6 3138.93   127.2 3130.17
   131.2  3129.2   172.5 3128.18   183.3 3127.06  191.79 3128.19   191.83128.195
   199.3 3130.78   219.3 3132.36   263.7 3131.54   339.5 3132.88   371.5 3138.01
   391.6 3142.34   403.6 3146.05   419.7 3153.08   439.8 3160.08   451.9 3165.88
   468.2 3165.91   477.1 3172.38   500.7  3180.1   561.6 3195.57   611.8 3210.07
#Mann= 5 ,-1,0
       0      .1       0   172.5    .045       0  191.79      .1       0
     410     .06       0   509.1      .1       0
Bank Sta=172.5,191.8
XS Rating Curve= 0 ,0
Exp/Cntr(USF)=0,0
Exp/Cntr=0.3,0.1

Type RM Length L Ch R = 1 ,4406    ,497.3,501,496.4
XS GIS Cut Line= 3
2345496.08935427635297.9951258682345791.79634096635554.475675549
2345958.76014978635513.237626385
#Sta/Elev= 30
       0 3159.99      16 3152.76    23.2 3151.35      42 3143.32    47.8 3142.14
    90.3 3128.98   121.9 3127.23   141.3 3125.16     181 3126.53   200.2 3125.51
   226.3 3126.12   264.9 3124.32   275.5 3123.75   291.3 3124.37   296.6 3125.86
   312.5 3125.93   319.9 3127.09   325.6 3129.17   339.7 3136.32   354.9 3141.11
   371.1 3144.17   395.9  3146.1   419.3 3150.65   437.2 3155.45   453.6 3156.58
   461.9 3158.29   477.7 3165.26   515.4 3179.52   548.4 3189.37   563.4  3194.5
#Mann= 8 ,-1,0
       0      .1       0     230     .12       0   264.9    .045       0
   291.3     .12       0     300     .06       0  421.44     .12       0
  441.44     .06       0  521.44      .1       0
Bank Sta=264.9,291.3
XS Rating Curve= 0 ,0
Exp/Cntr(USF)=0,0
Exp/Cntr=0.3,0.1

Type RM Length L Ch R = 1 ,3905    ,392.4,392.5,392.4
XS GIS Cut Line= 3
2345155.40002086635541.5302761922345588.82197563 635819.34397277
2345618.15128085635878.002583191
#Sta/Elev= 30
       0 3212.16    34.2 3197.11    91.2 3177.34   113.2  3166.2   129.2  3164.8
   140.2    3158   167.2  3146.7   176.7 3145.47   197.2 3139.23     229  3133.4
   236.5 3130.25   252.7 3120.92     267 3120.08   273.23118.793  273.21 3118.79
     281 3117.69   292.7 3118.79   304.3 3121.81   327.5 3123.07     343 3126.27
   376.3 3125.88   390.5 3124.56   405.7  3125.5   428.5 3132.29   443.3 3135.07
     457 3140.94   472.2 3141.41     495 3152.81   543.7 3166.78   580.4 3181.25
#Mann= 5 ,-1,0
       0      .1       0  273.21    .045       0   292.7      .1       0
     380     .12       0     440     .06       0
Bank Sta=273.2,292.7
XS Rating Curve= 0 ,0
Exp/Cntr(USF)=0,0
Exp/Cntr=0.3,0.1

Type RM Length L Ch R = 1 ,3512    ,441.9,444.9,450.5
XS GIS Cut Line= 2
2345006.97880586635909.0484641062345454.16018777636203.246741681
#Sta/Elev= 30
       0 3217.07    30.2 3202.57    44.5 3194.02    64.5 3184.53      78 3177.37
    90.5 3169.36   102.1 3167.78   122.3 3158.87   130.9 3152.93   145.1 3141.14
     180 3117.93   184.3 3115.93   188.7 3114.81   202.5 3114.65   211.3 3115.95
   237.8  3116.4   252.2 3118.43   264.8 3117.78   295.5 3118.92   313.2  3121.8
   331.8 3121.97   389.3  3146.9   405.3 3148.43   416.8 3156.38     437 3165.52
   451.5 3170.09   471.7 3178.88   495.1 3186.85   509.2 3193.47   535.3  3203.7
#Mann= 8 ,-1,0
       0      .1       0   184.3    .045       0   211.3      .1       0
     240     .08       0     270      .1       0     380     .07       0
     420     .06       0     500      .1       0
#XS Ineff= 2 , 0
                          251.67         3126.23
Permanent Ineff=
       F       F
Bank Sta=184.3,211.3
XS Rating Curve= 0 ,0
Exp/Cntr(USF)=0,0
Exp/Cntr=0.3,0.1

Type RM Length L Ch R = 1 ,3067    ,434.6,439.4,445.4
XS GIS Cut Line= 2
2344758.94702723636134.4496060022345011.50493321636539.990616321
#Sta/Elev= 30
       0 3228.43    36.2 3209.82    49.3 3201.45    62.9 3195.06   100.7 3171.83
   116.3 3165.22     151  3144.5     154 3143.08   163.4 3141.56   168.8 3139.02
   176.4 3134.27   205.8 3112.15   210.6 3111.55   221.8 3112.94   259.6 3110.87
   267.1 3109.35   278.7 3110.89   297.4 3113.89   319.4 3114.12   337.8 3115.68
   356.6 3120.86   366.1 3125.76   375.5 3133.93   388.2 3138.12   397.8 3144.48
   408.5 3146.06     421 3150.25   450.9 3164.43   460.3 3167.82   477.8 3176.51
#Mann= 6 ,-1,0
       0      .1       0   259.6    .045       0   278.7      .1       0
     330     .08       0     350     .06       0     470     .08       0
#XS Ineff= 2 , 0
          206.74 3125.01
Permanent Ineff=
       F       F
Bank Sta=259.6,278.7
XS Rating Curve= 0 ,0
Exp/Cntr(USF)=0,0
Exp/Cntr=0.3,0.1

Type RM Length L Ch R = 1 ,2628    ,485.8,486.8,488.4
XS GIS Cut Line= 2
2344502.76821937636261.1811717272344543.50336549636735.519317725
#Sta/Elev= 30
       0 3193.15    24.1 3181.48    44.2 3170.18    56.8 3166.46    75.2 3155.63
   100.4 3146.48   112.4 3139.04   120.4 3136.27   128.5  3131.4   144.5 3128.28
   156.6    3122   192.7 3110.84   200.7 3107.11   220.8 3105.21   240.9 3107.53
     265 3106.02   297.1 3108.22   318.43106.027  318.45 3106.02   333.2 3105.17
   341.4 3106.05   345.3 3108.39   353.3 3116.18   378.4 3133.23   393.4 3140.92
   409.5 3147.27   421.5 3154.42   437.6 3155.62   445.6 3163.81   476.1 3179.71
#Mann= 5 ,-1,0
       0      .1       0  318.45    .045       0   341.4      .1       0
     370     .06       0     470      .1       0
#XS Ineff= 2 , 0
          201.28 3120.27
Permanent Ineff=
       F       F
Bank Sta=318.4,341.4
XS Rating Curve= 0 ,0
Exp/Cntr(USF)=0,0
Exp/Cntr=0.3,0.1