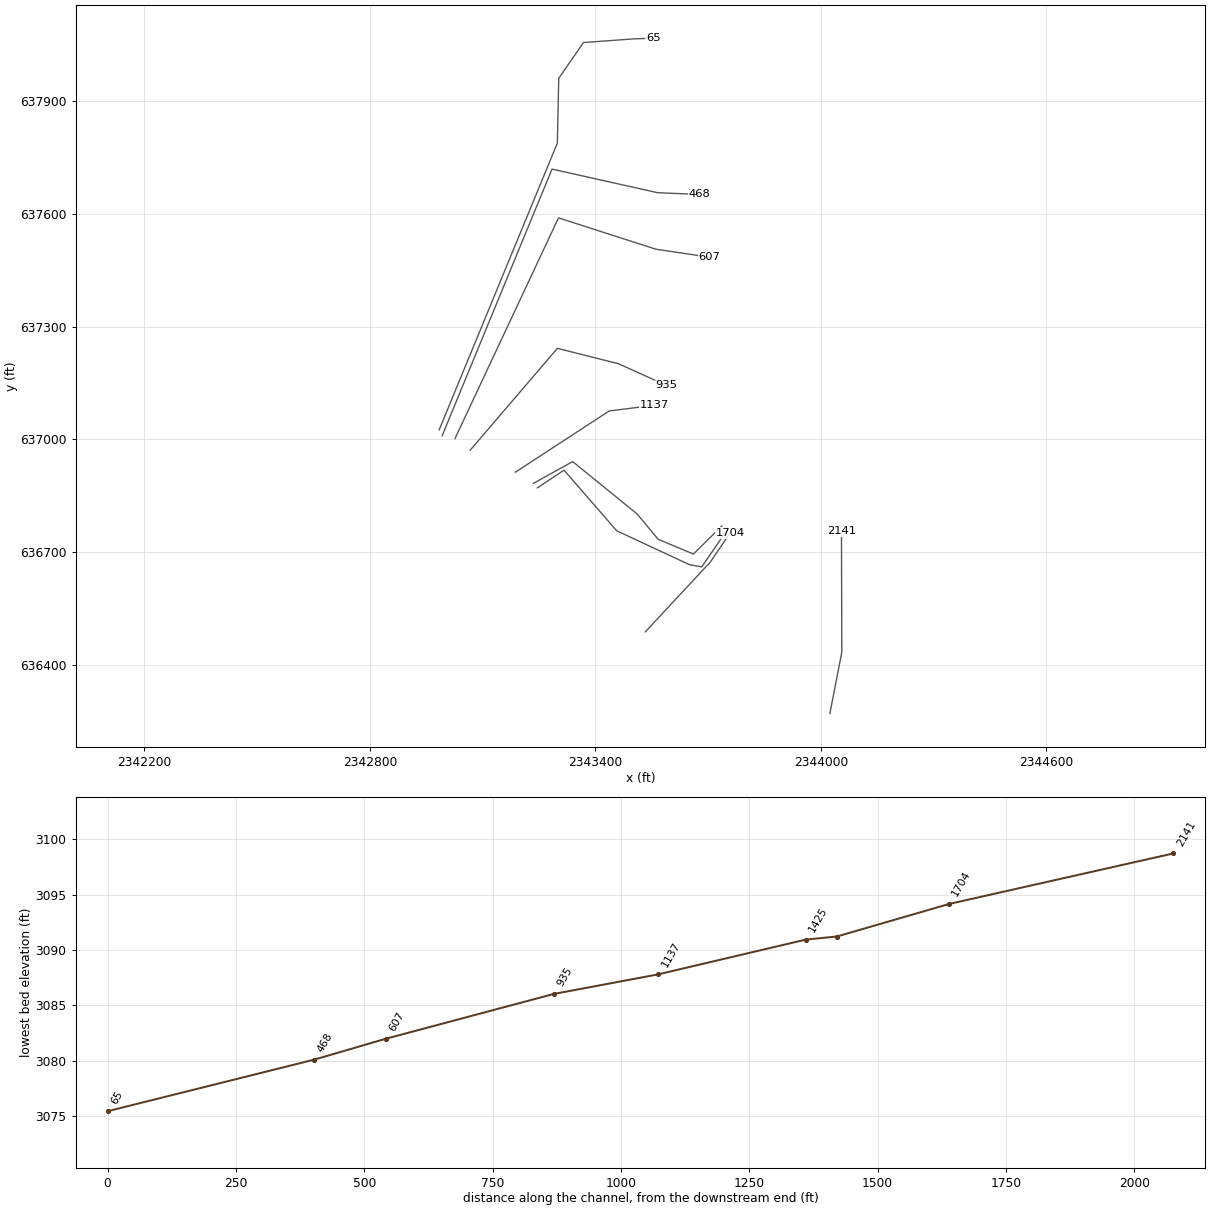
HEC-RAS study FIVELCKRN.prj: FIVELCKRN

--- FIVELCKRN.g01 (geometry) --- (continued)

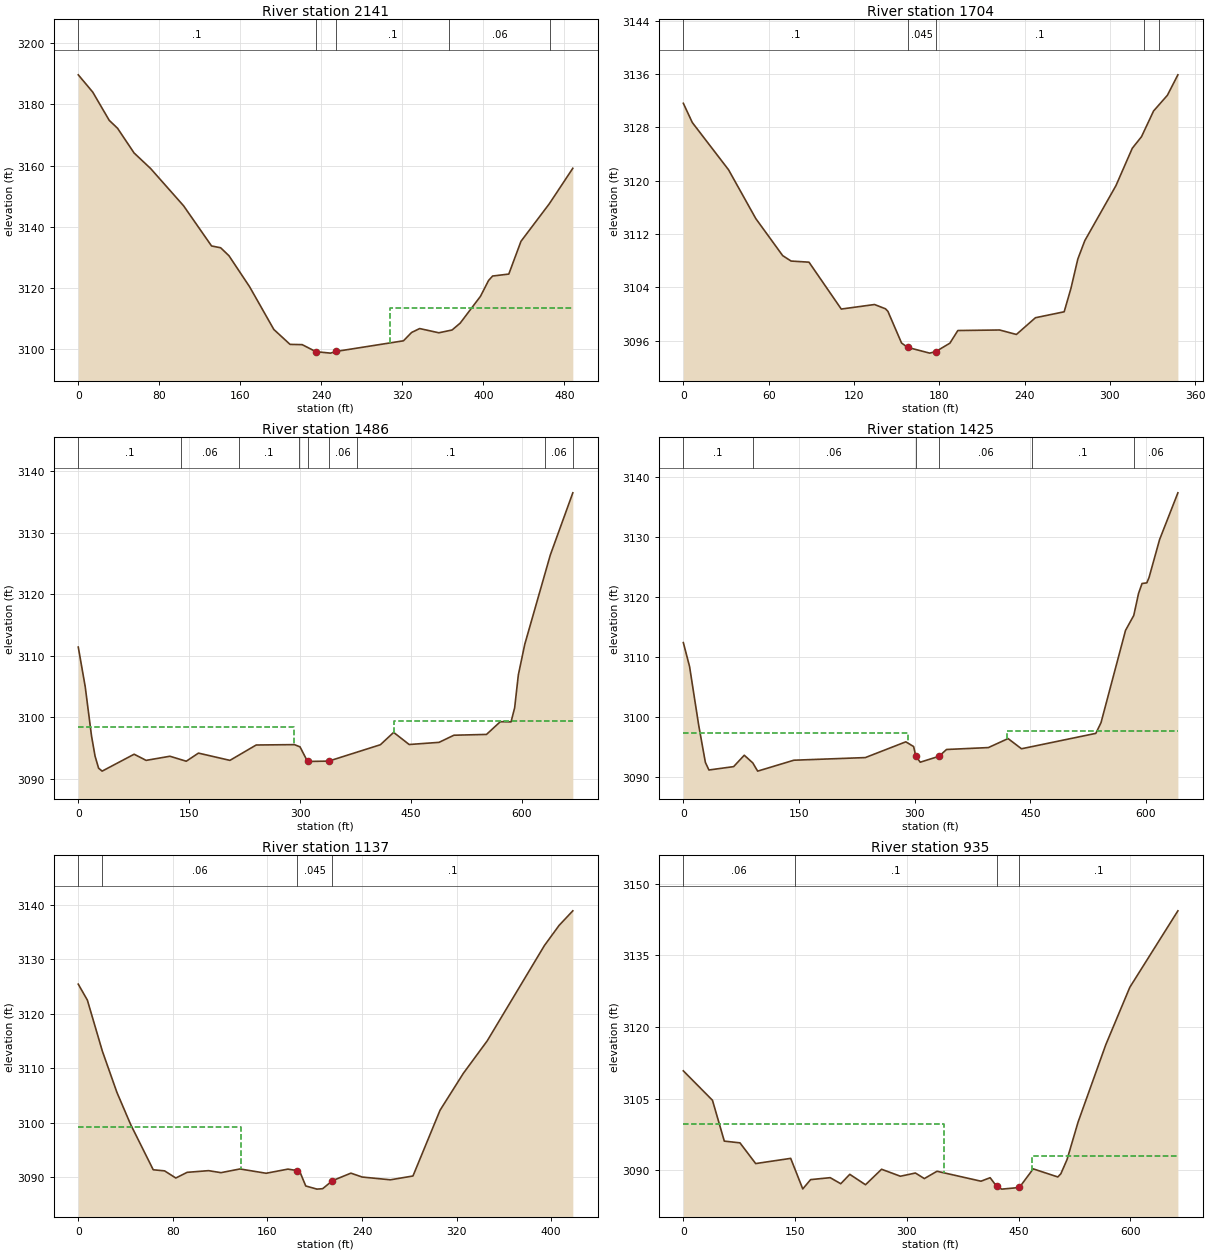
Type RM Length L Ch R = 1 ,2141    ,442.6,437.5,428.3
XS GIS Cut Line= 3
2344023.90394602636271.1386518912344055.58683745636434.079236394
2344054.68161199636756.339503523
#Sta/Elev= 30
       0 3189.67    14.3 3184.02    30.6 3174.78    38.8  3172.2    55.1 3164.13
    71.4 3159.06     104 3146.86   131.6 3133.74   140.6 3133.14   148.8 3130.54
   169.1 3120.44   193.1 3106.44   209.1 3101.57   221.1 3101.48   234.73099.175
   249.1 3098.71   254.63099.266   321.1 3102.74   329.1 3105.46   337.1 3106.74
     356 3105.36   369.1 3106.27   377.1 3108.52   397.1 3117.27   405.1 3122.45
   409.1 3123.91   425.1 3124.55   437.1 3135.25   465.1 3147.53   488.3 3159.13
#Mann= 5 ,-1,0
       0      .1       0   234.7    .045       0   254.6      .1       0
  365.99     .06       0  465.99      .1       0
#XS Ineff= 2 , 0
                          307.83          3113.6
Permanent Ineff=
       F       F
Bank Sta=234.7,254.6
XS Rating Curve= 0 ,0
Exp/Cntr(USF)=0,0
Exp/Cntr=0.3,0.1

Type RM Length L Ch R = 1 ,1704    ,232.7,218,206.7
XS GIS Cut Line= 3
2343532.54614499636487.8571735632343705.86740049636674.060414268
2343758.61859823636751.250054252
#Sta/Elev= 30
       0 3131.61     6.3 3128.73    31.8 3121.64      51 3114.31    69.9 3108.76
    75.8 3107.95    88.4 3107.78   111.1 3100.75   134.5 3101.43   142.2 3100.79
   143.9 3100.41   153.5 3095.66   157.7 3095.01   173.3 3094.14   177.53094.364
   187.5 3095.63   193.1 3097.53   222.5 3097.61   234.3 3096.94   247.7 3099.45
   267.9 3100.34   272.7 3103.88   277.5 3108.25   282.4    3111   304.3 3119.25
   315.8 3124.86   322.3  3126.6   330.8 3130.46   340.5 3132.81   347.9 3135.88
#Mann= 5 ,-1,0
       0      .1       0   157.7    .045       0   177.5      .1       0
  324.39     .06       0  334.39      .1       0
Bank Sta=157.7,177.5
XS Rating Curve= 0 ,0
Exp/Cntr(USF)=0,0
Exp/Cntr=0.3,0.1

Type RM Length L Ch R = 1 ,1486    ,62.8,60.7,60.3
XS GIS Cut Line= 6
2343245.26039602636871.0018959552343316.44640031636918.359216684
2343456.57530298636757.0480380262343650.47459854636666.616013627
2343683.06271544636660.9130931692343749.50735626636758.210823721
#Sta/Elev= 30
       0 3111.39     9.4 3104.95    17.9 3096.96    22.7 3093.66    27.5 3091.69
    32.3 3091.21    75.6 3093.96    91.8 3092.96     124 3093.63   146.1 3092.82
   162.6 3094.14   205.2 3092.96   240.7 3095.46   292.4 3095.52     300 3095.16
   310.2 3092.78   338.83092.839   408.7  3095.5   426.7 3097.51   447.7 3095.54
   488.1 3095.89   508.2 3097.05   552.3 3097.18     571 3099.25   585.5 3099.22
   590.4 3101.51   595.4 3106.87   604.1 3111.85   638.6 3126.35   669.1 3136.48
#Mann= 9 ,-1,0
       0      .1       0  139.61     .06       0  217.68      .1       0
  299.01     .06       0   310.2    .045       0   338.8     .06       0
  376.79      .1       0  631.28     .06       0   669.1      .1       0
#XS Ineff= 2 , 0
           291.9 3098.41  427.01         3099.32
Permanent Ineff=
       F       F
Bank Sta=310.2,338.8
XS Rating Curve= 0 ,0
Exp/Cntr(USF)=0,0
Exp/Cntr=0.3,0.1

Type RM Length L Ch R = 1 ,1425    ,264.6,287.6,294
XS GIS Cut Line= 6
2343235.12548329636883.1717840962343339.46401213636941.063012011
2343510.81985272636801.8566987642343567.03435437636734.236356196
2343660.72519046636695.1306159152343736.48097433636769.769499333
#Sta/Elev= 30
       0 3112.37     8.1 3108.37    19.9  3098.6    28.6 3092.38    33.2 3091.12
    65.2 3091.68      79 3093.58      90 3092.31    96.4 3090.93   143.3 3092.75
     236 3093.19   288.5 3095.82   298.6 3095.03   301.53093.433   307.2 3092.42
   331.6 3093.41   341.3 3094.54   395.6 3094.86   421.1 3096.36   438.5 3094.66
   534.9 3097.23   541.6 3099.01   573.4 3114.41   584.1 3116.91   590.3 3120.58
   594.8 3122.23     601 3122.34   603.9 3123.24   617.6 3129.57   641.3 3137.36
#Mann= 6 ,-1,0
       0      .1       0      90     .06       0   301.5    .045       0
   331.6     .06       0   452.2      .1       0  584.91     .06       0
#XS Ineff= 2 , 0
          291.34 3097.27  419.22         3097.65
Permanent Ineff=
       F       F
Bank Sta=301.5,331.6
XS Rating Curve= 0 ,0
Exp/Cntr(USF)=0,0
Exp/Cntr=0.3,0.1

Type RM Length L Ch R = 1 ,1137    ,215.9,202.7,191.8
XS GIS Cut Line= 3
2343187.07472356636912.9626853622343436.51680073637075.744134783
2343555.96793627637090.968299118
#Sta/Elev= 30
       0 3125.39     7.7 3122.46    20.4 3113.09    32.7 3105.53    44.3 3099.65
    63.4 3091.34      73 3091.14    82.5 3089.83    92.1 3090.87   110.2 3091.18
   120.7 3090.81   136.8 3091.49   158.9  3090.7   177.3 3091.46   185.23091.188
   187.6 3090.89   192.4 3088.37   201.9 3087.79   206.7 3087.87     215 3089.34
   230.6 3090.72   240.1 3090.01     264  3089.5   283.1  3090.2     306 3102.26
   325.7 3109.03   345.9 3114.99   394.3 3132.48   406.7 3136.17   418.3 3138.84
#Mann= 4 ,-1,0
       0      .1       0      20     .06       0   185.2    .045       0
     215      .1       0
#XS Ineff= 2 , 0
          137.52  3099.2
Permanent Ineff=
       F       F
Bank Sta=185.2,215
XS Rating Curve= 0 ,0
Exp/Cntr(USF)=0,0
Exp/Cntr=0.3,0.1

Type RM Length L Ch R = 1 ,935     ,328.3,327.7,327.5
XS GIS Cut Line= 4
2343066.78200724636971.4124846462343298.73716769637242.446492641
2343461.61439143637201.3729306822343588.34595715637144.041984282
#Sta/Elev= 30
       0 3110.79    39.1 3104.63      55 3096.08      76 3095.72    97.1 3091.38
   144.1 3092.47   160.3 3086.07   170.8 3088.02   197.1 3088.43   211.3 3087.16
   223.4 3089.13   244.5 3086.95   266.1 3090.19   291.3 3088.73   311.5  3089.4
   323.5 3088.24   340.5 3089.77   399.5 3087.69   411.8 3088.42   420.6  3086.6
   427.4 3086.03     4513086.371   469.6 3090.27   502.6 3088.58   506.7 3089.24
     515 3092.21   529.8 3100.05     567 3116.25   599.3 3128.29   663.8 3144.29
#Mann= 4 ,-1,0
       0     .06       0     150      .1       0   420.6    .045       0
     451      .1       0
#XS Ineff= 2 , 0
          349.36  3099.6  467.94         3092.88
Permanent Ineff=
       F       F
Bank Sta=420.6,451
XS Rating Curve= 0 ,0
Exp/Cntr(USF)=0,0
Exp/Cntr=0.3,0.1

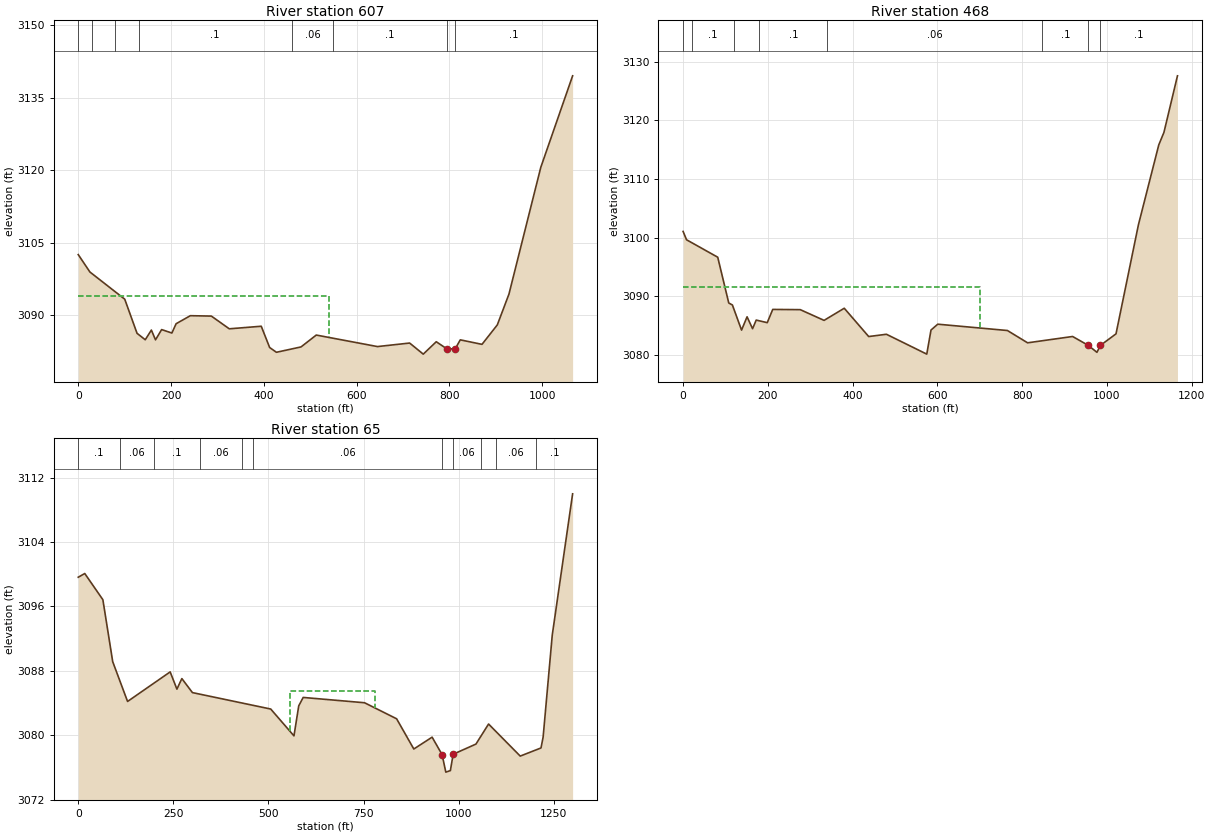
Type RM Length L Ch R = 1 ,607     ,137.6,139,139.2
XS GIS Cut Line= 4
2343026.34318408637002.4559848182343301.69122516637589.614076474
2343561.18919307637506.1321720682343704.01365603637485.010244447
#Sta/Elev= 30
       0 3102.54    25.1 3098.95   100.2 3093.33   126.7 3086.28   144.4 3084.95
   157.6 3086.95   166.5 3084.93   179.7 3087.05   201.8 3086.34   210.9 3088.26
   241.6 3089.92   286.9 3089.84   325.5 3087.21   394.4 3087.74   412.5 3083.35
   427.1 3082.36   480.2 3083.47     513 3085.92   644.9 3083.54   714.2 3084.27
   743.6 3081.98   771.6 3084.54   794.2 3083.09   812.33083.065   823.4 3084.93
   870.2    3084   903.2 3088.02   928.3 3094.38   996.9 3120.57  1065.5 3139.48
#Mann= 8 ,-1,0
       0     .06       0      30      .1       0      80     .06       0
     130      .1       0     460     .06       0     550      .1       0
   794.2    .045       0   812.3      .1       0
#XS Ineff= 2 , 0
          539.89 3094.08
Permanent Ineff=
       F       F
Bank Sta=794.2,812.3
XS Rating Curve= 0 ,0
Exp/Cntr(USF)=0,0
Exp/Cntr=0.3,0.1

Type RM Length L Ch R = 1 ,468     ,369.3,402.8,420.4
XS GIS Cut Line= 4
2342992.04192178637009.6447763022343284.47524679 637719.39395206
2343565.09514232637656.6618270252343676.16630742637651.954654584
#Sta/Elev= 30
       0 3101.04     8.1 3099.62    81.7 3096.64   107.7 3088.83   116.3 3088.49
   137.9  3084.2   150.9 3086.47   163.9 3084.44   172.5 3085.91   198.5 3085.47
   211.5 3087.73   276.4 3087.69   332.6 3085.86   380.2 3087.93   437.9  3083.1
   479.7 3083.49   574.9  3080.1   584.9 3084.21   600.8 3085.21   765.2 3084.13
   812.8 3082.03     919 3083.11   955.9  3081.6   976.4 3080.41   984.6 3081.59
  1021.4 3083.56  1074.3 3102.18  1122.3 3115.81  1134.5 3117.95  1166.4  3127.6
#Mann= 8 ,-1,0
       0     .06       0      20      .1       0     120     .06       0
     180      .1       0     340     .06       0  847.63      .1       0
   955.9    .045       0   984.6      .1       0
#XS Ineff= 2 , 0
          701.64  3091.6
Permanent Ineff=
       F       F
Bank Sta=955.9,984.6
XS Rating Curve= 0 ,0
Exp/Cntr(USF)=0,0
Exp/Cntr=0.3,0.1

Type RM Length L Ch R = 1 ,65      ,,,
XS GIS Cut Line= 6
2342984.13214174637025.3996145912343298.64904553637788.651864462
2343302.36784579637960.9697696362343368.11461605638056.115502204
 2343506.5570022638066.271507366 2343553.5953419638067.340560541
#Sta/Elev= 30
       0 3099.63    17.1 3100.09    64.7 3096.84    90.6 3089.14   129.6 3084.21
   241.6 3087.88   259.3 3085.74   272.3 3087.05   300.1 3085.31   505.9 3083.27
     567 3079.94   579.5 3083.66   591.2 3084.71   752.5 3084.05   836.8 3082.06
     882 3078.31   930.1 3079.78956.39093077.609   956.43077.604   966.1 3075.44
   978.1 3075.63985.36133077.651   985.43077.659  1045.3 3078.92  1078.5 3081.41
  1161.7 3077.43  1216.3 3078.44  1221.9 3079.79  1245.9 3092.45  1299.4 3109.98
#Mann= 11 ,-1,0
       0      .1       0     110     .06       0     200      .1       0
     320     .06       0     430      .1       0     460     .06       0
956.3909    .045       0985.3613     .06       0 1057.88      .1       0
 1097.88     .06       0 1203.53      .1       0
#XS Ineff= 2 ,-1
       0  314.69    3085     556   779.6 3085.55
Permanent Ineff=
       F       F
Bank Sta=956.4,985.4
XS Rating Curve= 0 ,0
Exp/Cntr(USF)=0,0
Exp/Cntr=0.3,0.1
LCMann Table=0

Chan Stop Cuts=-1
Use User Specified Reach Order=0
Composite Channel Slope=5